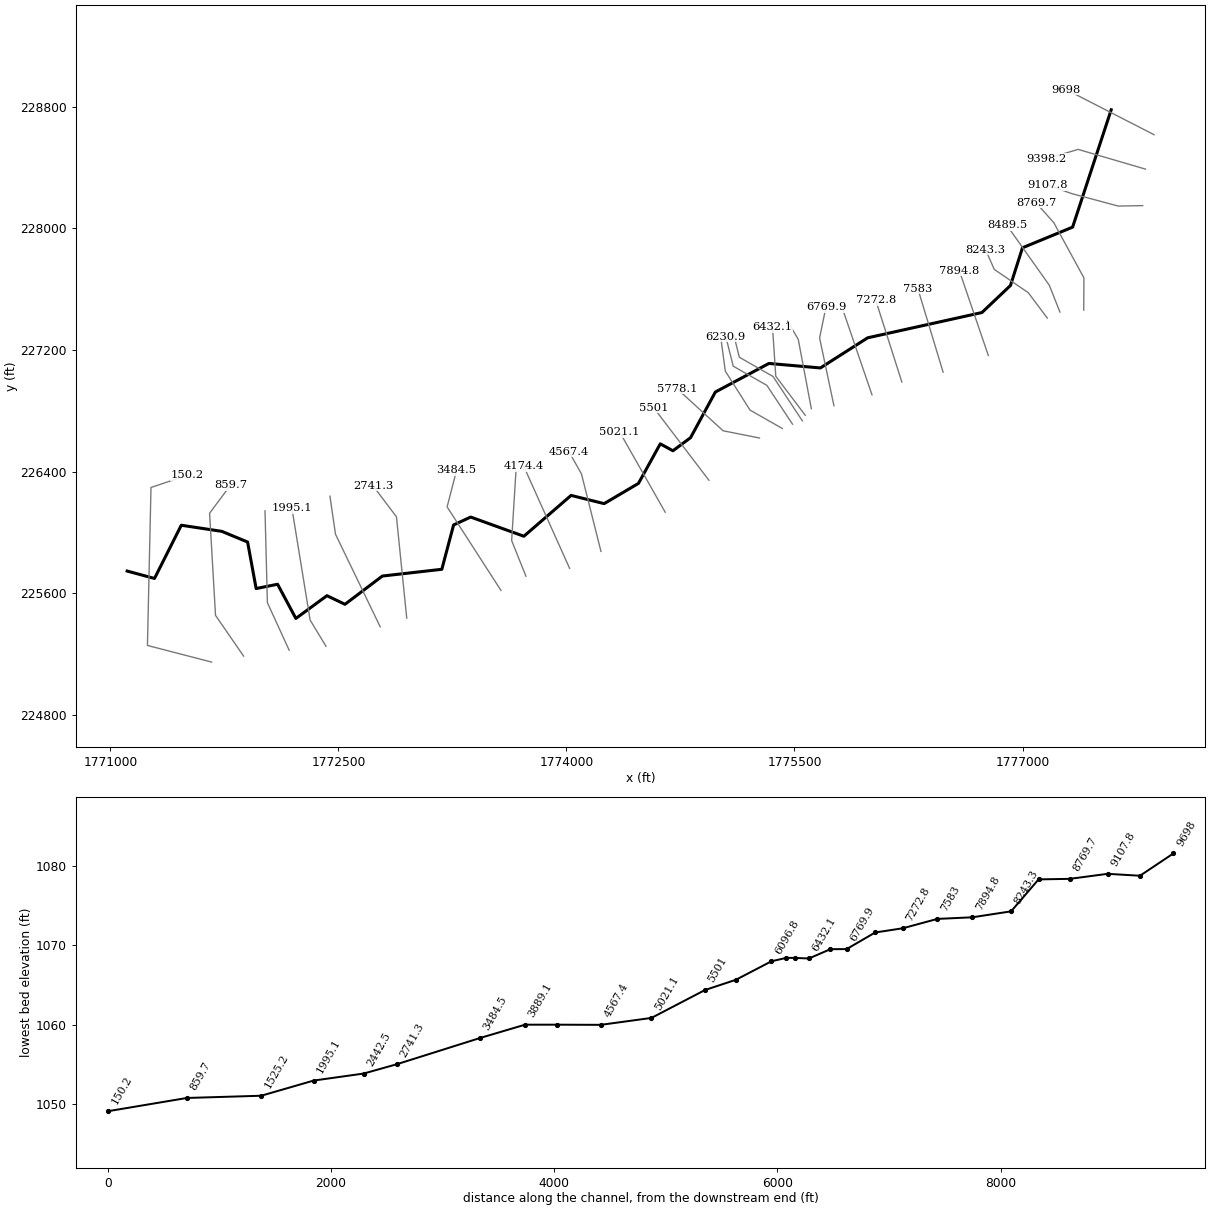
--- LEFTBR.prj (project) ---

Proj Title=LEFTBR
Current Plan=p01
Default Exp/Contr=0,0
English Units
Geom File=g01
Flow File=f01
Plan File=p01
BEGIN DESCRIPTION:
END DESCRIPTION:
DSS Export Rating Curves= 0
DSS Export Rating Curve Sorted= 0
DSS Export Volume Flow Curves= 0
DXF OffsetX= 0
DXF OffsetY= 0
DXF ScaleX= 0
DXF ScaleY= 0

--- LEFTBR.p01 (plan) ---

Plan Title=Floodplain
Program Version=4.00
Geom File=g01
Flow File=f01
K Sum by GR=0
Std Step Tol=0.01
Critical Tol=0.01
Num of Std Step Trials=20
Max Error Tol=0.3
Flow Tol Ratio=0.001
Split Flow NTrial=30
Split Flow Tol=0.02
Split Flow Ratio=0.02
Log Output Level=0
Friction Slope Method=1
Unsteady Friction Slope Method=2
Unsteady Bridges Friction Slope Method=1
Global Log Level=0
CheckData=False
Run HTab=0
Run UNet=0
Run PostProcess=0
UNET Theta=0
UNET Theta Warmup=0
UNET ZTol=0
UNET ZSATol=0
UNET MxIter=0
UNET MaxInSteps=0
UNET DtIC=0
UNET DtMin=0
UNET MaxCRTS=0
UNET WFStab=0
UNET SFStab=0
UNET WFX=0
UNET SFX=0
UNET DSS MLevel=0
UNET DZMax Abort=0
UNET Convert EG Bridges=0
UNET Use Existing IB Tables=0
UNET Froude Limit=0
UNET Froude Power=0
Write IC File=0
Echo Input=False
Echo Output=False
Write Detailed=0

--- LEFTBR.f01 (steady flow) ---

Flow Title=NFF Regression Equation
Program Version=4.00
Number of Profiles=1
Profile Names=P100yr
River Rch & RM=LEFTBR,Main      ,9698
790.0941
River Rch & RM=LEFTBR,Main      ,9398.2
791.7417
River Rch & RM=LEFTBR,Main      ,9107.8
1040.426
River Rch & RM=LEFTBR,Main      ,8489.5
1042.451
River Rch & RM=LEFTBR,Main      ,8243.3
1505.266
River Rch & RM=LEFTBR,Main      ,7025.4
1521.518
River Rch & RM=LEFTBR,Main      ,859.7
1689.834
River Rch & RM=LEFTBR,Main      ,150.2
1792.910
Boundary for River Rch & Prof#=LEFTBR,Main      ,1
Up Type=0
Dn Type=3
Dn Slope=0.002279

--- LEFTBR.g01 (geometry) ---

Geom Title=USGS 10m DEM
Program Version=4.10

River Reach=LEFTBR          ,Main
Reach XY= 30
     1777583.304      228780.772     1777329.458      228008.842
     1776999.655      227872.967     1776920.662       227624.92
     1776732.969      227447.041      1775981.15      227280.715
     1775670.401      227082.554     1775331.752      227112.167
     1774979.581      226924.291     1774816.171      226623.655
      1774700.32      226537.778     1774617.091      226583.305
     1774473.641      226323.227     1774247.839      226189.978
     1774030.549      226244.159     1773719.827      225975.471
     1773370.209      226101.701     1773257.587      226049.829
     1773180.133       225758.05     1772789.106      225713.724
     1772542.929      225527.792     1772424.548      225584.562
     1772219.978      225434.756     1772099.764      225659.704
     1771958.726       225631.38     1771902.498      225937.485
     1771733.054      226007.624     1771466.387      226047.902
     1771290.102      225697.854     1771110.137      225746.513

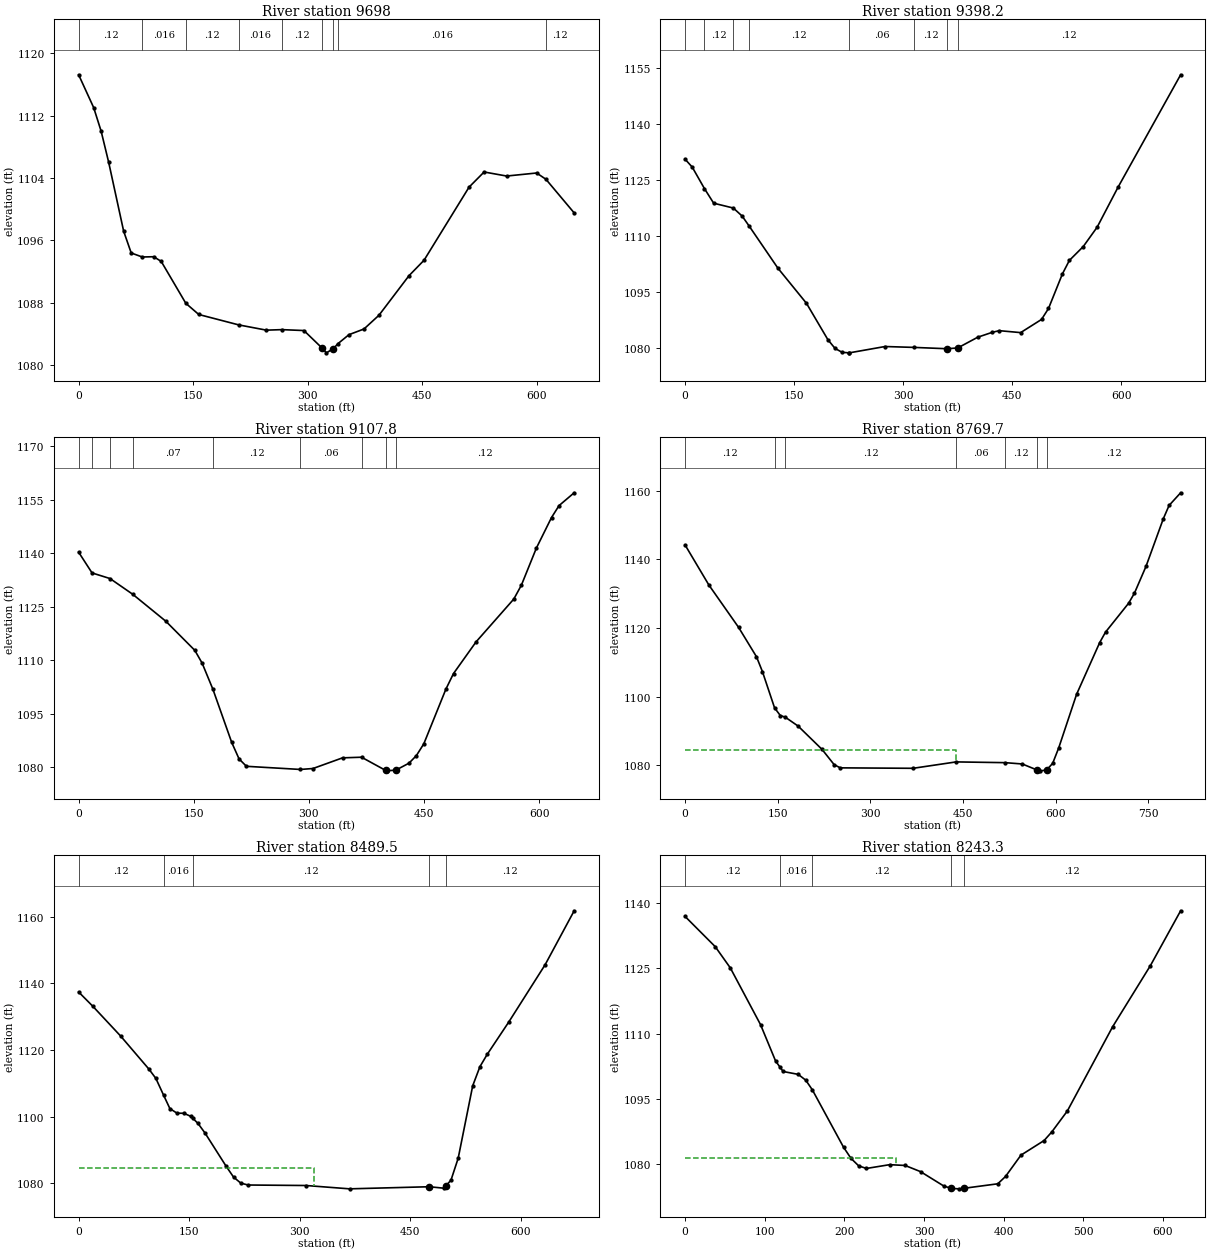
Type RM Length L Ch R = 1 ,9698    ,294.9,299.8,303.6
XS GIS Cut Line= 2
      1777865.32       228616.74     1777287.663      228913.295
#Sta/Elev= 30
       0 1117.23    19.7 1113.02    29.5 1109.99    39.4 1105.99      59 1097.16
    68.9 1094.37   83.361093.855    98.4 1093.89   108.2 1093.29  140.451087.915
   157.4 1086.48  209.771085.145     246 1084.47  266.411084.537   295.2 1084.42
   318.8 1082.19   324.7 1081.56   333.8  1082.1  339.811082.741   354.2 1083.89
   373.9 1084.62   393.5 1086.38   432.9 1091.46   452.6 1093.44   511.6 1102.82
   531.3 1104.76   560.8 1104.24   600.1 1104.63  612.261103.828   649.3 1099.51
#Mann= 9 ,-1 , 0
       0     .12       0   83.36    .016       0  140.45     .12       0
  209.77    .016       0  266.41     .12       0   318.8    .045       0
   333.8     .12       0  339.81    .016       0  612.26     .12       0
Bank Sta=318.8,333.8
XS Rating Curve= 0 ,0
Exp/Cntr=0.3,0.1

Type RM Length L Ch R = 1 ,9398.2  ,289.8,290.4,290.8
XS GIS Cut Line= 3
     1777808.833      228390.447     1777366.037      228520.186
       1777155.1      228457.686
#Sta/Elev= 30
       0 1130.53     9.8 1128.43    26.61122.681    39.3 1118.77   66.331117.477
    78.5 1115.32   87.86 1112.72   127.6  1101.4   166.9    1092   196.4 1082.25
   206.2 1079.93     216 1078.88   225.8 1078.75  226.041078.755   274.9 1080.44
  315.141080.201   359.8 1079.85   374.8 1080.05   402.5 1082.94   422.1 1084.22
     432 1084.68   461.4 1084.16   490.1 1087.68   499.7 1090.61   518.8 1099.85
   528.4 1103.47   547.5 1107.18   566.6 1112.36   595.3 1123.04   681.4 1153.12
#Mann= 8 ,-1 , 0
       0     .06       0    26.6     .12       0   66.33    .016       0
   87.86     .12       0  226.04     .06       0  315.14     .12       0
   359.8    .045       0   374.8     .12       0
Bank Sta=359.8,374.8
XS Rating Curve= 0 ,0
Exp/Cntr=0.3,0.1

Type RM Length L Ch R = 1 ,9107.8  ,354.3,338.1,317.8
XS GIS Cut Line= 4
     1777790.516      228150.394     1777629.656      228147.418
     1777322.827      228229.637     1777165.516      228285.811
#Sta/Elev= 30
       0 1140.27   17.481134.455   40.881132.883   70.431128.483   113.6 1120.92
   151.4 1112.75   160.9 1109.17  174.971101.834   199.4 1086.97     209 1082.34
   218.6 1080.26  288.86 1079.38   305.3 1079.64   343.8 1082.63  368.571082.809
   399.9 1079.12   401.5 1078.99  413.371079.197   430.4 1081.14     440 1083.25
   449.7 1086.56   478.5  1101.9   488.4 1106.26   517.8 1115.14     567 1127.15
   576.8 1131.01   596.4 1141.44   616.1 1149.99   625.9 1153.33   645.6 1156.92
#Mann= 9 ,-1 , 0
       0     .12       0   17.48    .016       0   40.88     .12       0
   70.43     .07       0  174.97     .12       0  288.86     .06       0
  368.57     .12       0   399.9    .045       0  413.37     .12       0
Bank Sta=399.9,413.37
XS Rating Curve= 0 ,0
Exp/Cntr=0.3,0.1

Type RM Length L Ch R = 1 ,8769.7  ,277.5,280.1,282.7
XS GIS Cut Line= 4
     1777402.495      227462.894      1777404.05      227674.752
      1777206.43      228037.036      1777088.54      228170.126
#Sta/Elev= 30
       0 1144.23    38.5 1132.56    86.7 1120.18   115.6 1111.63   125.2 1107.31
  144.841096.734   154.1  1094.5  162.151094.014     183 1091.41   221.7 1084.62
   241.3 1080.17   251.2 1079.23   369.1  1079.1  438.861080.966  518.241080.746
   545.9 1080.36  570.36 1078.57   575.4 1078.36   585.2  1078.6   595.1 1080.54
   604.9 1085.05   633.9 1100.71   671.3 1115.79   680.7 1118.82   718.1 1127.25
   727.5 1130.18   746.2 1137.98   774.3 1151.91   783.6 1155.77   802.3 1159.46
#Mann= 7 ,-1 , 0
       0     .12       0  144.84    .016       0  162.15     .12       0
  438.86     .06       0  518.24     .12       0  570.36    .045       0
   585.2     .12       0
#XS Ineff= 2 , 0
           438.6 1084.49
Permanent Ineff=
       F       F
Bank Sta=570.36,585.2
XS Rating Curve= 0 ,0
Exp/Cntr=0.3,0.1

Type RM Length L Ch R = 1 ,8489.5  ,238.7,246.2,252.8
XS GIS Cut Line= 3
     1777246.245      227449.874     1777175.933      227626.957
     1776897.287      228020.186
#Sta/Elev= 30
       0 1137.41      19 1133.18    57.2 1124.13    95.3 1114.27   104.8 1111.46
  115.391106.376   123.8 1102.41   133.4 1101.02   142.9 1100.98   152.4 1100.04
  155.021099.464     162 1097.93   171.5 1095.06   200.4    1085   210.2 1081.83
     220 1080.02   229.9 1079.44   308.6 1079.29   367.6 1078.29   475.8 1078.92
   495.4 1078.49  498.411079.217   505.3 1080.88   515.1 1087.49   534.8 1109.24
   544.6 1114.98   554.4 1118.65     584 1128.48   633.1  1145.6   672.5  1161.8
#Mann= 5 ,-1 , 0
       0     .12       0  115.39    .016       0  155.02     .12       0
   475.8    .045       0  498.41     .12       0
#XS Ineff= 2 , 0
           319.3 1084.53
Permanent Ineff=
       F       F
Bank Sta=475.8,498.41
XS Rating Curve= 0 ,0
Exp/Cntr=0.3,0.1

Type RM Length L Ch R = 1 ,8243.3  ,361.8,348.5,334.4
XS GIS Cut Line= 4
     1777162.912      227410.811     1777037.912      227577.478
     1776813.954      227731.124     1776756.662      227861.332
#Sta/Elev= 30
       0 1136.94    37.9 1129.98    56.8  1125.1    94.7 1112.06   113.6 1103.69
  119.37 1102.22   123.1 1101.27     142 1100.61   151.5 1099.27  159.751097.056
   198.9 1083.86   208.3 1081.28     218 1079.55   227.7 1078.96   256.8 1079.83
   276.2 1079.65   295.6 1078.23   324.7 1074.93   334.4 1074.36   344.1 1074.27
   350.3  1074.4   392.6 1075.43   402.3 1077.11   421.7 1082.02   450.8 1085.39
   460.5 1087.38   479.9 1092.17   536.8 1111.56   584.2 1125.62   622.2 1138.25
#Mann= 5 ,-1 , 0
       0     .12       0  119.37    .016       0  159.75     .12       0
   334.4    .045       0   350.3     .12       0
#XS Ineff= 2 , 0
          265.12 1081.35
Permanent Ineff=
       F       F
Bank Sta=334.4,350.3
XS Rating Curve= 0 ,0
Exp/Cntr=0.3,0.1

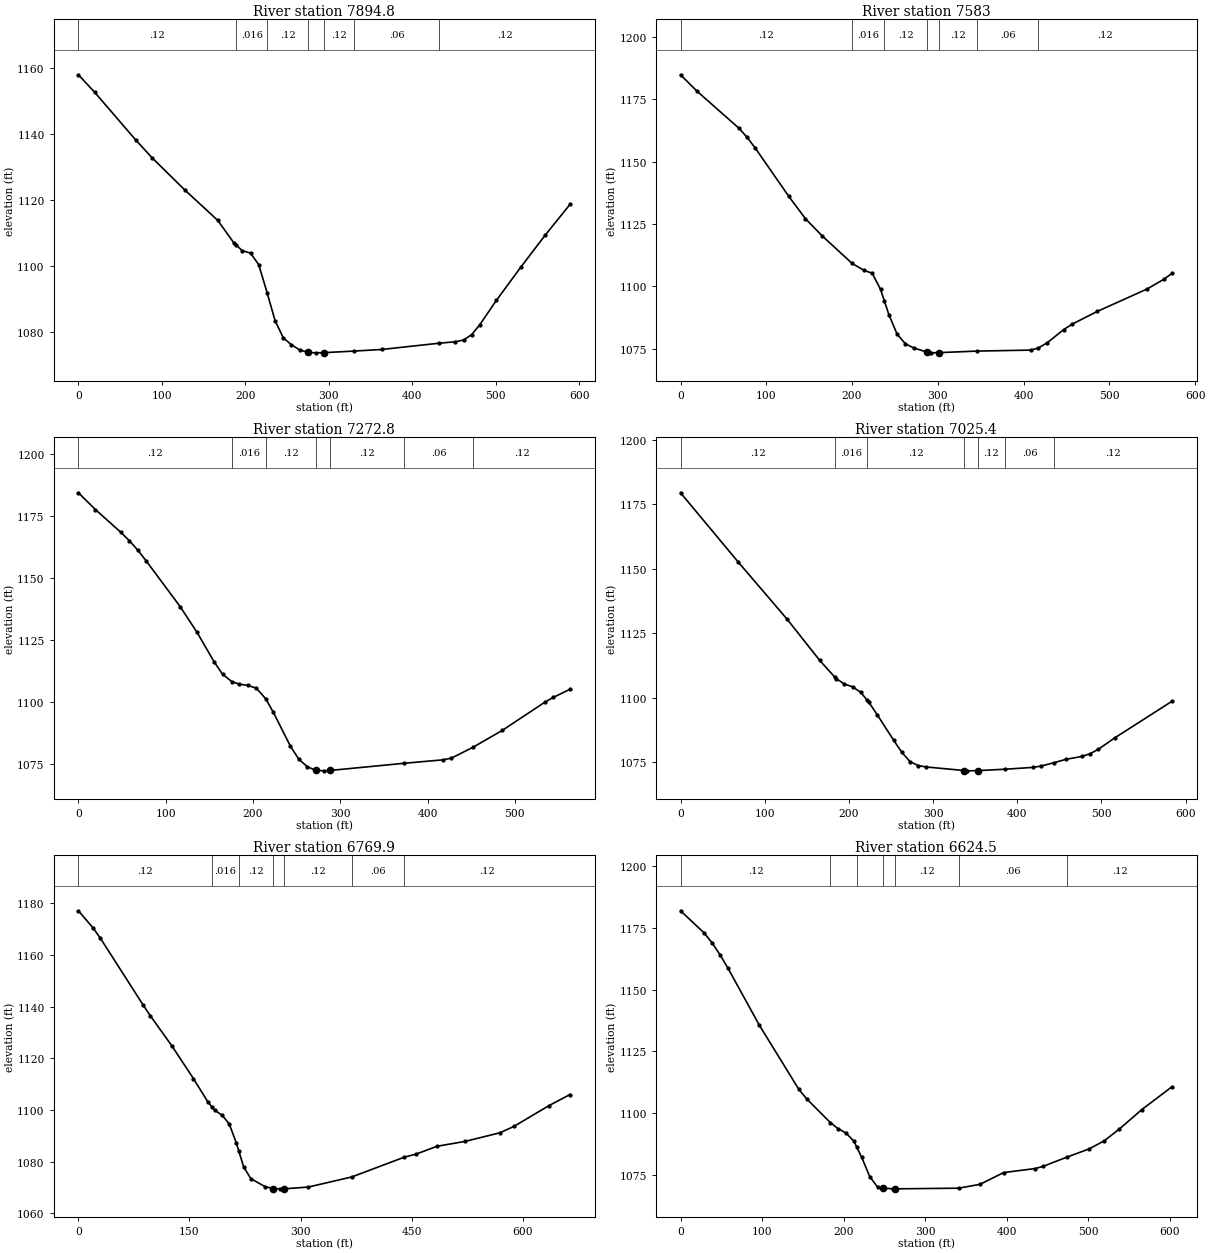
Type RM Length L Ch R = 1 ,7894.8  ,312.1,311.8,310.3
XS GIS Cut Line= 2
     1776775.077      227164.637     1776584.399      227721.926
#Sta/Elev= 30
       0 1158.02    19.6 1152.66    68.7  1138.2    88.4 1132.75   127.6 1122.99
   166.9 1113.78   186.5 1106.85  188.891106.294   196.3 1104.57   206.2 1103.82
     216 1100.33  226.221091.666   235.6 1083.31   245.4 1078.12   255.2 1075.95
     265 1074.43   274.9 1073.66   284.7 1073.52   294.5 1073.58  329.991074.053
   363.2 1074.54  432.511076.454   451.6 1076.89   461.4  1077.4   471.2 1079.07
     481 1082.09   500.7 1089.44   530.1 1099.58   559.6 1109.39     589 1118.64
#Mann= 7 ,-1 , 0
       0     .12       0  188.89    .016       0  226.22     .12       0
   274.9    .045       0   294.5     .12       0  329.99     .06       0
  432.51     .12       0
Bank Sta=274.9,294.5
XS Rating Curve= 0 ,0
Exp/Cntr=0.3,0.1

Type RM Length L Ch R = 1 ,7583    ,304.6,310.2,309.4
XS GIS Cut Line= 2
     1776477.689      227054.687     1776311.645      227603.359
#Sta/Elev= 30
       0 1184.85    19.4 1178.21      68 1163.44    77.7 1159.74    87.4 1155.32
   126.3 1136.04   145.7  1127.1   165.2 1120.21  200.111109.181   213.8 1106.43
   223.5 1105.26   233.2 1098.78  237.791094.001   242.9 1088.68   252.6 1080.76
   262.3 1076.92     272 1075.27  287.721073.594   291.5 1073.32   301.2  1073.4
  345.791074.023   408.1 1074.42   417.11075.246   427.5 1077.34   446.9 1082.68
   456.6 1084.82   485.8 1089.91   544.1 1098.94   563.5 1102.82   573.2 1105.24
#Mann= 7 ,-1 , 0
       0     .12       0  200.11    .016       0  237.79     .12       0
  287.72    .045       0   301.2     .12       0  345.79     .06       0
   417.1     .12       0
Bank Sta=287.72,301.2
XS Rating Curve= 0 ,0
Exp/Cntr=0.3,0.1

Type RM Length L Ch R = 1 ,7272.8  ,246.6,247.5,248.2
XS GIS Cut Line= 2
     1776206.201      226989.864     1776034.979      227526.499
#Sta/Elev= 30
       0 1184.19    19.4 1177.45    48.6 1168.25    58.3 1164.91      68 1161.06
    77.7 1156.72   116.5 1138.35     136  1127.9   155.4 1116.12   165.1 1111.09
  175.72  1108.1   184.5 1107.05   194.2 1106.58     204  1105.4  214.471101.259
   223.4 1095.68   242.8 1082.13   252.5 1076.85   262.2  1073.8   271.9 1072.35
   281.6 1072.14  288.211072.287   373.41075.195   417.6 1076.57   427.3 1077.25
  452.161081.638   485.6 1088.42   534.2 1099.74   543.9  1101.7   563.3    1105
#Mann= 7 ,-1 , 0
       0     .12       0  175.72    .016       0  214.47     .12       0
   271.9    .045       0  288.21     .12       0   373.4     .06       0
  452.16     .12       0
Bank Sta=271.9,288.21
XS Rating Curve= 0 ,0
Exp/Cntr=0.3,0.1

Type RM Length L Ch R = 1 ,7025.4  ,257.8,255.5,250.1
XS GIS Cut Line= 2
     1776009.785      226905.591     1775820.741      227458.077
#Sta/Elev= 30
       0 1179.51    68.1 1152.79   126.5 1130.49   165.4 1114.43  183.35 1107.94
   184.9  1107.4   194.6  1105.3   204.4 1104.21   214.1 1102.05  221.891098.934
   223.8 1098.17   233.6 1093.39     253 1083.56   262.8  1078.8   272.5 1075.22
   282.2 1073.66     292 1073.11  336.741071.734   340.6 1071.61  352.981071.694
  385.281072.239   418.5 1072.94   428.2 1073.48  443.731074.776   457.4 1076.05
   476.9  1077.2   486.6 1078.28   496.3 1079.98   515.8 1084.41   583.9 1098.64
#Mann= 7 ,-1 , 0
       0     .12       0  183.35    .016       0  221.89     .12       0
  336.74    .045       0  352.98     .12       0  385.28     .06       0
  443.73     .12       0
Bank Sta=336.74,352.98
XS Rating Curve= 0 ,0
Exp/Cntr=0.3,0.1

Type RM Length L Ch R = 1 ,6769.9  ,145.6,145.4,146.2
XS GIS Cut Line= 3
      1775759.52      226833.928     1775665.053      227280.119
     1775707.183      227483.728
#Sta/Elev= 30
       0 1177.04    19.4 1170.55    29.1 1166.68    87.3 1140.65      97 1136.48
   126.2  1124.8   155.3 1112.18   174.7 1103.18  179.991101.353   184.4 1099.83
   194.1    1098   203.8 1094.55   213.5 1087.07  216.78    1084   223.2 1077.99
   232.9 1073.43   252.3 1070.34   263.3 1069.65   271.7 1069.52   278.3 1069.53
   310.5 1070.21  369.311074.125  440.261081.778   456.1 1082.96   484.4 1085.98
   522.2 1087.86   569.5 1091.21   588.4 1093.69   635.6  1101.7     664 1105.99
#Mann= 7 ,-1 , 0
       0     .12       0  179.99    .016       0  216.78     .12       0
   263.3    .045       0   278.3     .12       0  369.31     .06       0
  440.26     .12       0
Bank Sta=263.3,278.3
XS Rating Curve= 0 ,0
Exp/Cntr=0.3,0.1

Type RM Length L Ch R = 1 ,6624.5  ,194.8,192.4,190.1
XS GIS Cut Line= 3
     1775610.829      226814.457     1775524.891      227270.186
     1775454.579      227389.978
#Sta/Elev= 30
       0  1181.8      29 1172.82    38.6 1168.88    48.3 1164.08      58  1158.7
    96.6  1135.6   144.9 1109.75   154.6 1105.87  183.711096.261   193.2  1093.8
   202.9 1092.07   212.6  1088.7  215.751086.567   222.2  1082.2   231.9 1074.48
   241.5 1070.26     248  1069.8   260.9 1069.51     263 1069.51  340.86 1069.77
   367.1 1071.32   396.1 1076.08   434.8 1077.71   444.4 1078.57  474.051082.365
   500.8 1085.61   519.3 1088.86   537.8  1093.6   565.6 1101.53   602.7 1110.77
#Mann= 7 ,-1 , 0
       0     .12       0  183.71    .016       0  215.75     .12       0
     248    .045       0     263     .12       0  340.86     .06       0
  474.05     .12       0
Bank Sta=248,263
XS Rating Curve= 0 ,0
Exp/Cntr=0.3,0.1

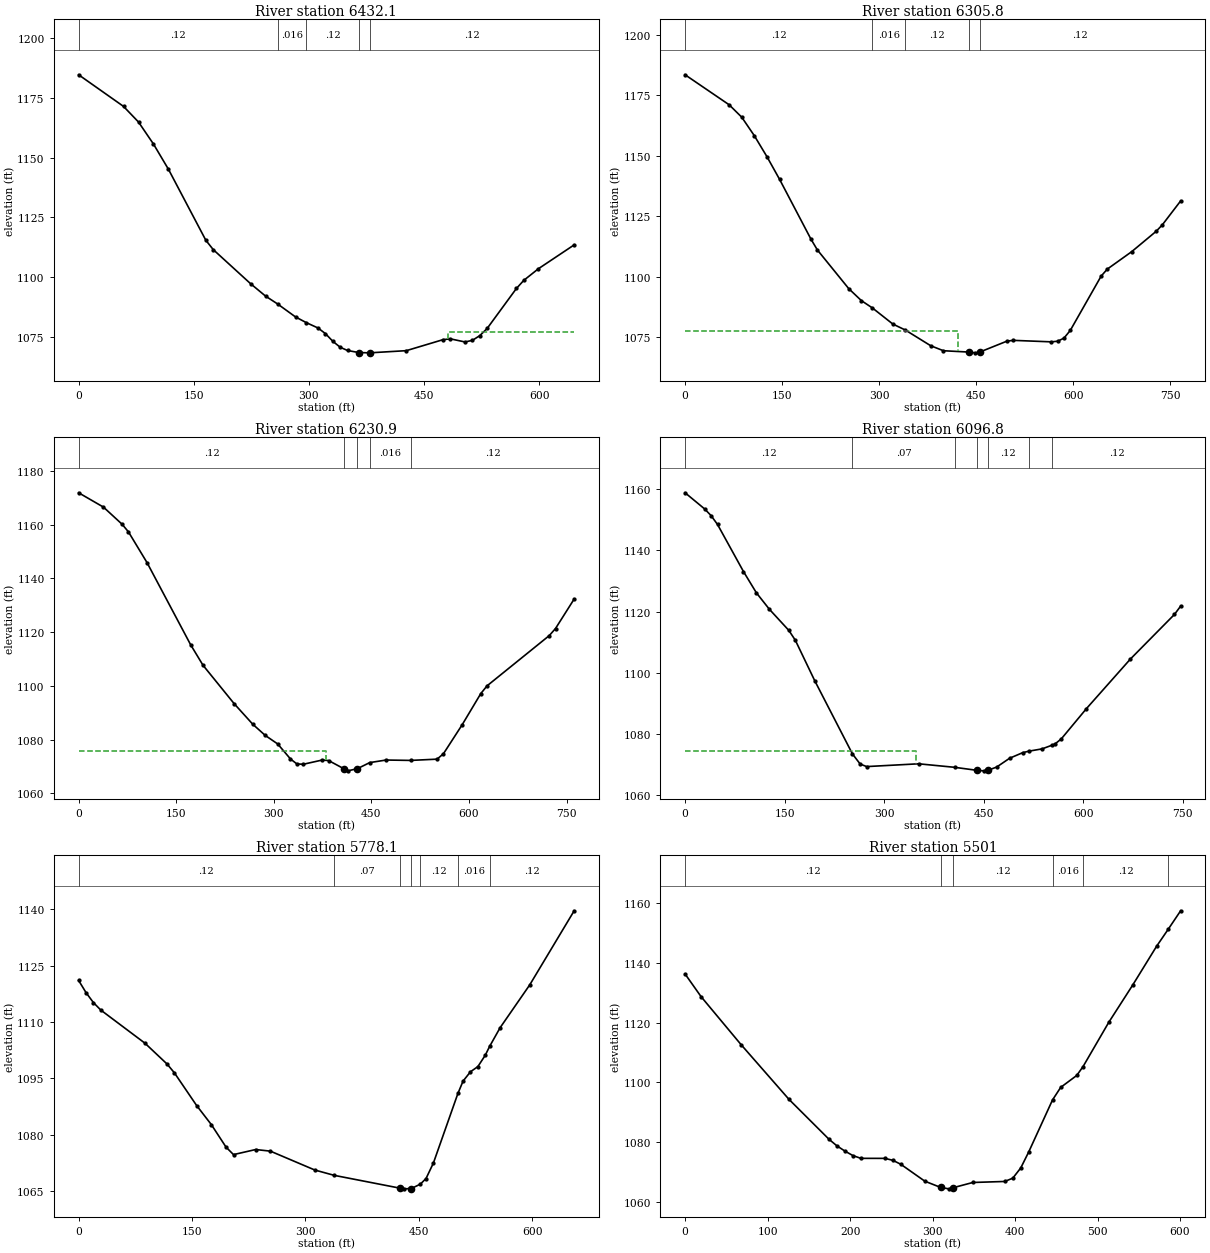
Type RM Length L Ch R = 1 ,6432.1  ,96.7,126.3,150.6
XS GIS Cut Line= 4
     1775570.898      226771.367     1775376.888      227027.877
     1775356.054      227342.981     1775352.633      227350.402
#Sta/Elev= 30
       0 1184.65    58.5 1171.42      78 1164.89    97.5 1155.68     117 1145.13
   165.7 1115.44   175.4 1111.51   224.2 1097.21   243.6 1092.06  259.341088.758
   282.6 1083.35  296.751080.955   311.9 1078.73   321.6 1076.36   331.2 1073.16
   340.8 1070.67   350.3 1069.32  365.09 1068.46     379 1068.34   426.9 1069.25
   474.7 1073.85   484.3 1074.19   503.4 1072.89     513 1073.57   522.6 1075.52
   532.2 1078.53   570.4 1095.28     580 1098.67   599.1 1103.54   645.6  1113.5
#Mann= 5 ,-1 , 0
       0     .12       0  259.34    .016       0  296.75     .12       0
  365.09    .045       0     379     .12       0
#XS Ineff= 2 , 0
                          481.11         1077.26
Permanent Ineff=
       F       F
Bank Sta=365.09,379
XS Rating Curve= 0 ,0
Exp/Cntr=0.3,0.1

Type RM Length L Ch R = 1 ,6305.8  ,75.3,74.9,73.6
XS GIS Cut Line= 4
     1775551.844      226734.321     1775358.659      227026.575
     1775137.304      227152.877     1775098.195      227308.771
#Sta/Elev= 30
       0 1183.57    68.1 1171.14    87.6 1165.99     107 1158.34   126.5 1149.65
     146 1140.28   194.6 1115.46   204.4 1111.04     253 1094.98   272.5 1090.03
  289.591086.982   321.1 1080.33   340.41077.856   379.7 1071.34   399.3 1069.28
   438.6 1068.73   448.4 1068.41  455.03 1068.69   497.4 1073.25   507.2 1073.58
     566 1072.96   575.8 1073.22   585.6 1074.51   595.4 1077.72     643 1100.17
   652.5 1103.08   690.3 1110.32   728.1 1118.75   737.6 1121.42   765.9 1131.32
#Mann= 5 ,-1 , 0
       0     .12       0  289.59    .016       0   340.4     .12       0
   438.6    .045       0  455.03     .12       0
#XS Ineff= 2 , 0
          421.05  1077.5
Permanent Ineff=
       F       F
Bank Sta=438.6,455.03
XS Rating Curve= 0 ,0
Exp/Cntr=0.3,0.1

Type RM Length L Ch R = 1 ,6230.9  ,145.3,134.1,122.9
XS GIS Cut Line= 4
     1775487.029      226712.716     1775318.294      226967.981
      1775096.94      227094.283     1775048.063      227289.111
#Sta/Elev= 30
       0 1171.88    38.2 1166.54    66.9 1160.15    76.5 1157.36   105.2 1145.87
   172.1 1115.36   191.2  1107.7   239.1  1093.4   267.7 1085.75   286.9 1081.59
     306 1078.42   325.6 1072.85   335.4    1071   345.2 1070.86   374.6 1072.45
   384.4 1072.23  408.331069.122   413.8 1068.42  428.63 1069.24  447.431071.487
   472.6 1072.44  510.441072.299     551 1072.77   560.8  1074.8   589.5 1085.55
   618.2 1097.18   627.8 1100.05   723.4 1118.74     733 1121.37   761.7 1132.35
#Mann= 5 ,-1 , 0
       0     .12       0  408.33    .045       0  428.63     .12       0
  447.43    .016       0  510.44     .12       0
#XS Ineff= 2 , 0
          379.77 1075.81
Permanent Ineff=
       F       F
Bank Sta=408.33,428.63
XS Rating Curve= 0 ,0
Exp/Cntr=0.3,0.1

Type RM Length L Ch R = 1 ,6096.8  ,310.3,318.8,324.4
XS GIS Cut Line= 4
     1775420.042      226684.498     1775207.617      226805.221
     1775044.857      227061.731     1775018.332      227258.968
#Sta/Elev= 30
       0 1158.83    29.3 1153.58    39.1 1151.39    48.9 1148.47      88  1133.1
   107.5 1126.14     127 1120.79   156.4 1113.87   166.2 1110.65   195.5 1097.41
  252.351073.504   263.9 1070.22   273.7 1069.38   352.1 1070.29  406.351069.141
   440.3 1068.15   450.1 1067.99  456.371068.158   469.7 1069.22   489.3 1072.11
   508.9 1073.92  517.971074.401   538.3 1075.17  553.521076.395   557.6 1076.76
   567.1 1078.41     605  1088.3   671.3  1104.5   737.7 1119.07   747.1  1121.8
#Mann= 7 ,-1 , 0
       0     .12       0  252.35     .07       0  406.35     .12       0
   440.3    .045       0  456.37     .12       0  517.97    .016       0
  553.52     .12       0
#XS Ineff= 2 , 0
          347.57 1074.36
Permanent Ineff=
       F       F
Bank Sta=440.3,456.37
XS Rating Curve= 0 ,0
Exp/Cntr=0.3,0.1

Type RM Length L Ch R = 1 ,5778.1  ,282.2,277.1,273.3
XS GIS Cut Line= 3
     1775269.683      226621.749     1775030.426      226669.226
     1774726.542      226946.932
#Sta/Elev= 30
       0 1121.06     9.8 1117.82    19.5 1115.19    29.3 1113.19    87.8 1104.37
   117.1 1098.82   126.8 1096.47   156.1 1087.81   175.6 1082.73   195.1 1076.73
   204.9 1074.76   234.2 1076.11   253.7 1075.68   312.5 1070.66  338.171069.244
  425.271065.835   430.2 1065.66     440 1065.73  452.041066.903   459.6  1068.4
   469.4 1072.54  501.761091.006   508.6  1094.3   518.4 1096.78   528.2 1098.16
     538 1101.18  543.721103.521   557.6 1108.49   596.8 1119.88   655.6 1139.58
#Mann= 7 ,-1 , 0
       0     .12       0  338.17     .07       0  425.27    .045       0
     440     .07       0  452.04     .12       0  501.76    .016       0
  543.72     .12       0
Bank Sta=425.27,440
XS Rating Curve= 0 ,0
Exp/Cntr=0.3,0.1

Type RM Length L Ch R = 1 ,5501    ,478,479.8,474
XS GIS Cut Line= 2
     1774937.174      226343.652     1774573.304      226821.555
#Sta/Elev= 30
       0  1136.3    19.4 1128.71    67.8 1112.67   125.9 1094.34   174.4 1080.98
   184.1 1078.75   193.8    1077   203.4 1075.51   213.1 1074.58   242.2 1074.57
   251.9 1073.92   261.6 1072.57   290.6 1066.93     310 1064.82   319.7 1064.37
  324.461064.715   348.8  1066.5   387.5 1066.84   397.2 1067.94   406.9 1071.37
   416.6 1076.76   445.41094.139   455.3 1098.34   474.7 1102.32  482.361105.281
   513.5 1120.09   542.5 1132.56   571.6 1145.61  585.561151.249   600.7 1157.47
#Mann= 6 ,-1 , 0
       0     .12       0     310    .045       0  324.46     .12       0
   445.4    .016       0  482.36     .12       0  585.56     .06       0
Bank Sta=310,324.46
XS Rating Curve= 0 ,0
Exp/Cntr=0.3,0.1

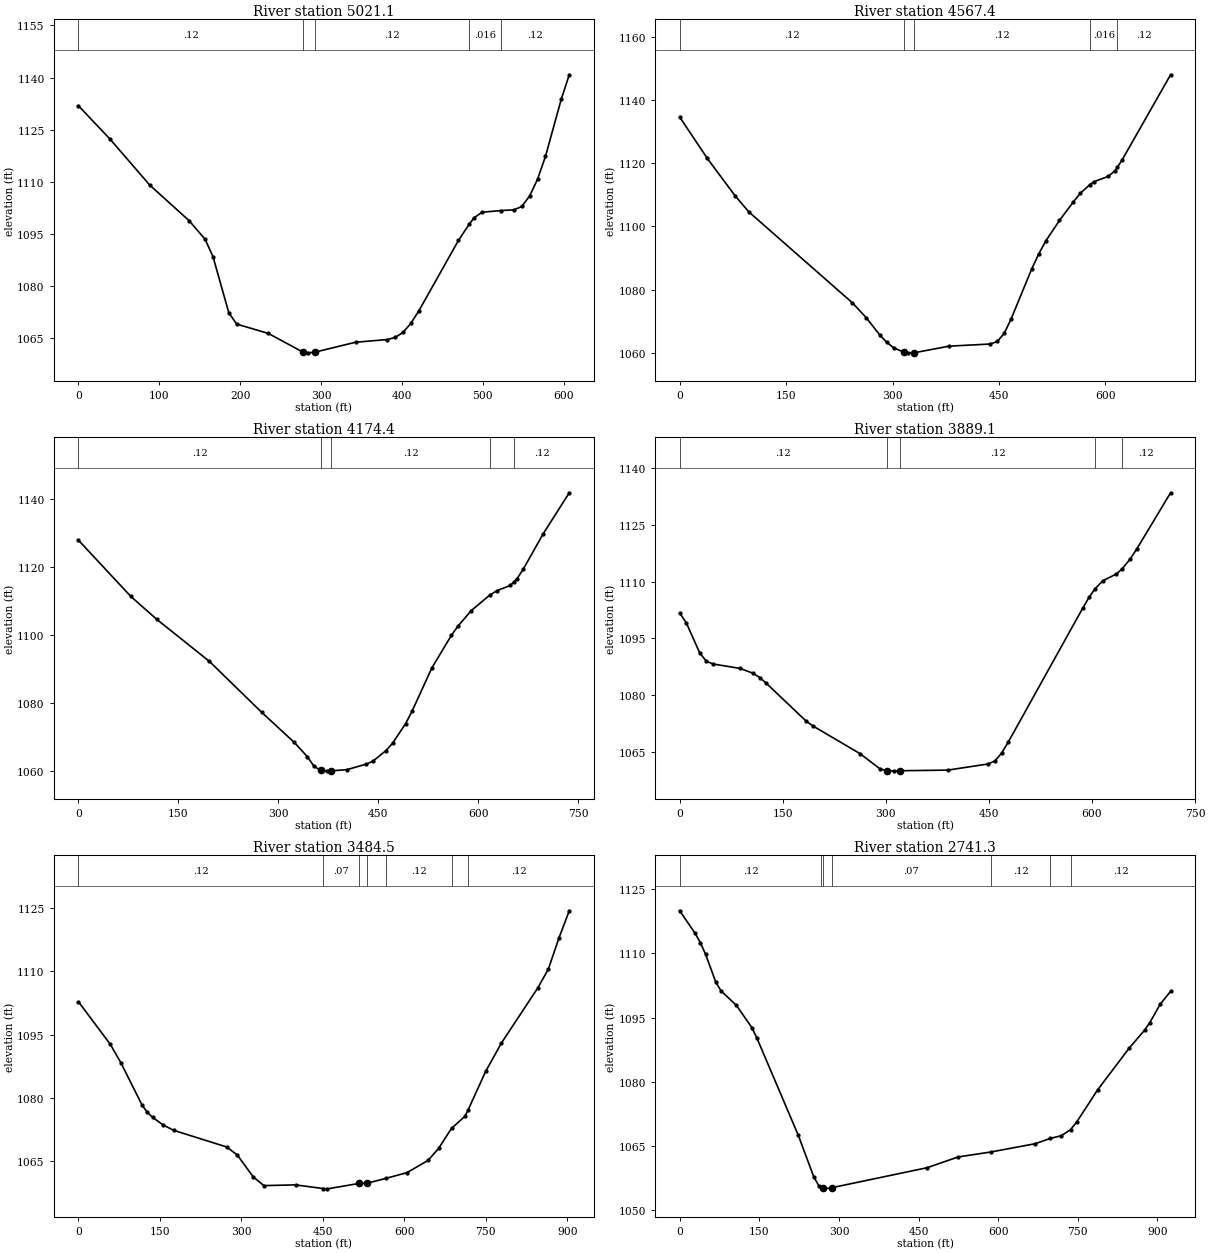
Type RM Length L Ch R = 1 ,5021.1  ,459,453.7,447.5
XS GIS Cut Line= 2
     1774649.465      226133.617     1774349.967      226661.215
#Sta/Elev= 30
       0  1131.9    39.1 1122.29    88.1  1109.1     137 1098.82   156.6  1093.5
   166.4  1088.5   185.9 1072.38   195.7 1069.12   234.8 1066.43     277 1061.14
   283.8 1060.86     292 1061.04   342.5  1063.9   381.6 1064.68   391.4 1065.28
   401.2 1066.72     411 1069.37   420.8 1072.92   469.7 1093.16  483.171097.889
   489.3 1099.74     499 1101.27  521.821101.757   538.2 1101.96     548 1102.93
   557.8 1105.97   567.5 1110.76   577.3 1117.33   596.9 1133.82   606.7 1140.79
#Mann= 5 ,-1 , 0
       0     .12       0     277    .045       0     292     .12       0
  483.17    .016       0  521.82     .12       0
Bank Sta=277,292
XS Rating Curve= 0 ,0
Exp/Cntr=0.3,0.1

Type RM Length L Ch R = 1 ,4567.4  ,376.4,393,397.4
XS GIS Cut Line= 3
     1774226.977      225876.007     1774098.655       226385.62
     1774017.079      226530.603
#Sta/Elev= 30
       0 1134.63    38.9 1121.55    77.8 1109.79    97.3 1104.64   243.3 1075.85
   262.8 1071.16   282.2 1065.58     292 1063.31   301.7 1061.55   316.31060.178
   321.2 1059.99   330.9 1060.03   379.5  1062.1   437.9 1062.79   447.7  1063.6
   457.4 1066.16   467.1  1070.7   496.3 1086.62   506.1 1091.31   515.8 1095.34
   535.3 1101.91   554.9 1107.79   564.7 1110.51  578.041113.236   584.2 1114.21
   603.8 1115.83   613.6 1117.64  617.061118.823   623.4 1120.99   691.9 1148.03
#Mann= 5 ,-1 , 0
       0     .12       0   316.3    .045       0   330.9     .12       0
  578.04    .016       0  617.06     .12       0
Bank Sta=316.3,330.9
XS Rating Curve= 0 ,0
Exp/Cntr=0.3,0.1

Type RM Length L Ch R = 1 ,4174.4  ,297.3,285.3,272.6
XS GIS Cut Line= 2
     1774020.617      225764.525     1773718.707        226436.4
#Sta/Elev= 30
       0 1127.89    78.6 1111.34   117.8 1104.55   196.4 1092.25     275 1077.24
   324.1 1068.35   343.7 1064.15   353.6 1061.35   363.4 1060.15   373.2 1060.01
  379.491060.014   402.7 1060.35   432.1 1061.99     442 1062.85   461.6 1065.98
   471.4 1068.12   491.1 1073.92   500.9 1077.64   530.4 1090.29   559.8  1099.9
   569.6  1102.6   589.3 1107.12  617.281111.719   628.6 1113.07   648.2 1114.56
  653.471115.582     658 1116.46   667.8 1119.43   697.3  1129.7   736.6 1141.83
#Mann= 5 ,-1 , 0
       0     .12       0   363.4    .045       0  379.49     .12       0
  617.28    .016       0  653.47     .12       0
Bank Sta=363.4,379.49
XS Rating Curve= 0 ,0
Exp/Cntr=0.3,0.1

Type RM Length L Ch R = 1 ,3889.1  ,388.8,404.6,419.5
XS GIS Cut Line= 3
     1773733.225      225712.894     1773639.475      225947.269
      1773668.12      226408.207
#Sta/Elev= 30
       0 1101.71     9.7 1099.07    29.1 1091.17    38.8 1088.97    48.5 1088.24
    87.4 1087.08   106.8  1085.8   116.5 1084.65   126.2 1083.11   184.5 1073.06
   194.2 1071.83   262.3 1064.56   291.7  1060.5   301.6 1060.05   311.4 1060.01
   321.2 1060.04     390  1060.2     449 1061.83   458.8 1062.65   468.6 1064.74
   478.4  1067.7   586.5    1103   596.3 1106.03  604.261108.088     616 1110.27
   635.6 1112.02  643.541113.343   655.3 1115.92   665.1 1118.62   714.3 1133.47
#Mann= 5 ,-1 , 0
       0     .12       0   301.6    .045       0   321.2     .12       0
  604.26    .016       0  643.54     .12       0
Bank Sta=301.6,321.2
XS Rating Curve= 0 ,0
Exp/Cntr=0.3,0.1

Type RM Length L Ch R = 1 ,3484.5  ,743.4,743.2,679.4
XS GIS Cut Line= 3
     1773569.162      225619.144     1773214.995      226168.624
     1773277.495      226410.811
#Sta/Elev= 30
       0 1102.81    58.5 1092.72    78.1 1088.33   117.1 1078.27   126.8 1076.52
   136.6 1075.32   156.1  1073.5   175.6 1072.23   273.2 1068.27   292.7 1066.36
     322 1061.15   341.5  1059.1     400 1059.27  451.081058.391   458.6 1058.33
   517.1 1059.62  532.011059.674  567.141060.854   604.9 1062.17     644  1065.1
   663.4 1067.97  686.991072.697   711.4 1075.53   717.41077.033   749.9 1086.25
   778.8 1092.95   846.1 1106.13   865.4 1110.57   884.6 1117.87   903.8 1124.41
#Mann= 7 ,-1 , 0
       0     .12       0  451.08     .07       0   517.1    .045       0
  532.01     .07       0  567.14     .12       0  686.99    .016       0
   717.4     .12       0
Bank Sta=517.1,532.01
XS Rating Curve= 0 ,0
Exp/Cntr=0.3,0.1

Type RM Length L Ch R = 1 ,2741.3  ,295,298.8,306.2
XS GIS Cut Line= 3
      1772949.37      225436.853     1772881.662      226103.519
     1772728.016      226306.644
#Sta/Elev= 30
       0 1119.93    29.1 1114.65    38.8 1112.52    48.6 1109.82      68 1103.27
    77.7 1101.26   106.8 1097.86     136 1092.65   145.7 1090.14   223.4 1067.54
   252.5 1057.86   262.2 1055.74  266.871055.399  269.031055.245   271.9 1055.04
  286.611055.308   466.2 1059.97   524.4 1062.48  586.211063.639   670.1 1065.58
   697.81066.793   719.1 1067.45  736.411068.858   748.5 1070.75   787.6 1078.18
   846.4 1087.81   875.8 1092.07   885.6 1093.81   905.2 1098.12   924.8 1101.12
#Mann= 7 ,-1 , 0
       0     .12       0  266.87     .07       0  269.03    .045       0
  286.61     .07       0  586.21     .12       0   697.8    .016       0
  736.41     .12       0
Bank Sta=269.03,286.61
XS Rating Curve= 0 ,0
Exp/Cntr=0.3,0.1

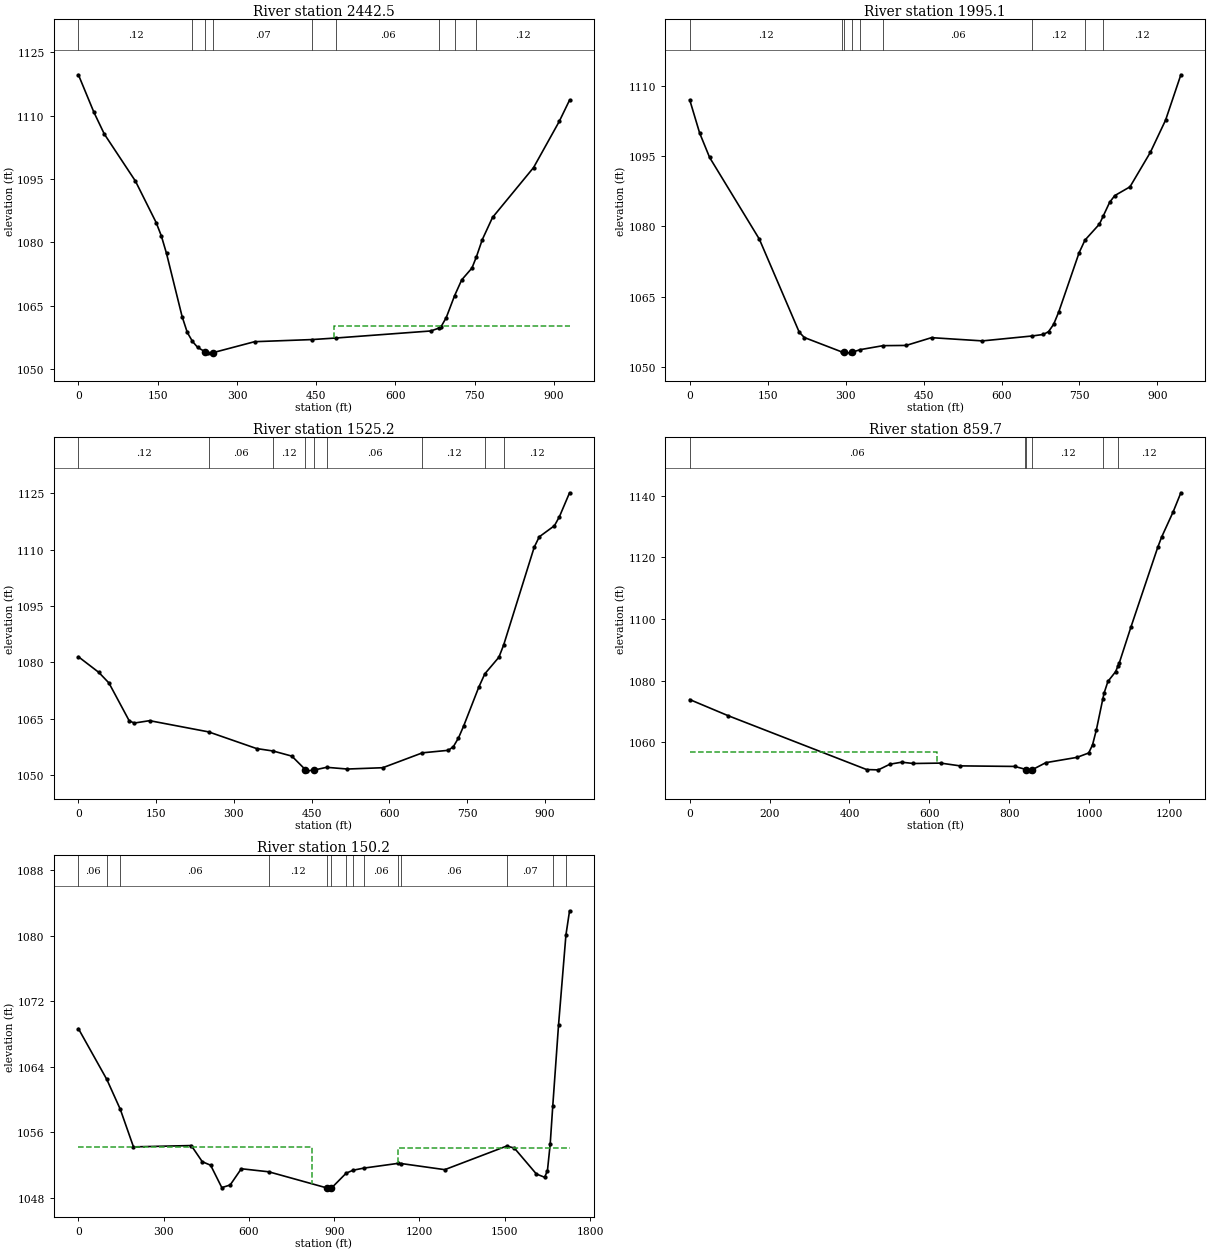
Type RM Length L Ch R = 1 ,2442.5  ,455.5,447.4,440.7
XS GIS Cut Line= 3
     1772774.891      225379.561      1772480.62      225988.936
     1772444.162      226238.936
#Sta/Elev= 30
       0 1119.71    29.4 1110.81      49 1105.68   107.9 1094.53   147.1 1084.72
   156.9 1081.56   166.7  1077.4   196.2 1062.46     206  1058.7  215.841056.564
   225.6 1055.16  240.261054.059   245.2 1053.86     255 1053.91   333.4  1056.5
  442.091057.003  487.271057.371   666.9 1059.04  682.381059.728   686.4 1060.08
   696.1 1062.22  711.72 1067.36   725.3 1071.14   744.7 1073.94  753.161076.609
   764.2 1080.66   783.6 1085.92   861.3 1097.74   909.9 1108.67   929.4 1113.71
#Mann= 9 ,-1 , 0
       0     .12       0  215.84     .07       0  240.26    .045       0
     255     .07       0  442.09     .12       0  487.27     .06       0
  682.38     .12       0  711.72    .016       0  753.16     .12       0
#XS Ineff= 2 , 0
                             484         1060.29
Permanent Ineff=
       F       F
Bank Sta=240.26,255
XS Rating Curve= 0 ,0
Exp/Cntr=0.3,0.1

Type RM Length L Ch R = 1 ,1995.1  ,471.1,470,464.5
XS GIS Cut Line= 3
      1772418.12      225251.957     1772313.954      225423.832
     1772194.162      226158.207
#Sta/Elev= 30
       0 1106.99    19.1 1099.91    38.3 1094.69     134 1077.25   210.8 1057.38
   220.6 1056.25  292.971053.162     297 1053.06   308.7 1052.98     312 1053.07
  327.561053.651   372.21054.514   416.4 1054.56   465.3 1056.22   563.2 1055.53
  659.351056.585   680.7 1056.91   690.5 1057.51   700.3 1059.07   710.1 1061.71
   749.2 1074.32  760.561077.042   788.4 1080.46   795.4 1082.11     808  1085.1
   817.8 1086.54   847.2 1088.42   886.3 1095.76   915.7 1102.66   945.1 1112.34
#Mann= 9 ,-1 , 0
       0     .12       0  292.97     .08       0     297    .045       0
     312     .08       0  327.56     .12       0   372.2     .06       0
  659.35     .12       0  760.56    .016       0   795.4     .12       0
Bank Sta=297,312
XS Rating Curve= 0 ,0
Exp/Cntr=0.3,0.1

Type RM Length L Ch R = 1 ,1525.2  ,661,665.4,666.8
XS GIS Cut Line= 3
     1772175.933      225225.915     1772032.704      225538.415
     1772017.079      226142.582
#Sta/Elev= 30
       0 1081.45    39.3  1077.3    58.9 1074.47    98.2 1064.36     108  1063.8
   137.5 1064.43   251.41061.442   343.8 1057.01  376.031056.344     412 1054.99
  438.251051.371   441.2 1051.07  454.221051.262  479.161052.009   519.2 1051.55
   587.5  1051.9  664.081055.867   714.2 1056.54   723.9 1057.53   733.7 1059.84
   743.4 1062.92   772.7  1073.3  784.591076.917   811.7 1081.33  820.841084.571
   879.9 1110.64   889.6 1113.39   918.9 1116.35   928.6 1118.78   948.1 1125.12
#Mann= 9 ,-1 , 0
       0     .12       0   251.4     .06       0  376.03     .12       0
  438.25    .045       0  454.22     .12       0  479.16     .06       0
  664.08     .12       0  784.59    .016       0  820.84     .12       0
Bank Sta=438.25,454.22
XS Rating Curve= 0 ,0
Exp/Cntr=0.3,0.1

Type RM Length L Ch R = 1 ,859.7   ,705.9,709.5,703.1
XS GIS Cut Line= 4
     1771876.454      225186.853     1771691.558      225455.082
     1771652.495      226126.957     1771790.516      226311.853
#Sta/Elev= 30
       0  1073.9    95.8 1068.69   442.8 1051.21   472.1  1051.1   501.4 1052.95
   530.6 1053.59   559.9 1053.17   628.2  1053.3   676.9  1052.4   813.5 1052.22
  838.191051.364   842.7 1051.08   852.5 1050.79  857.15 1051.13   891.5 1053.44
   969.5 1055.16   998.8 1056.58  1008.4 1059.21    1018 1064.08 1034.051074.043
  1037.2 1075.94  1046.9 1079.77  1066.1 1082.93  1071.9 1084.73  1075.7 1085.91
  1104.5  1097.4  1171.8 1123.32  1181.4 1126.59  1210.3 1134.79  1229.5 1140.94
#Mann= 6 ,-1 , 0
       0     .06       0  838.19     .12       0   842.7    .045       0
  857.15     .12       0 1034.05    .016       0  1071.9     .12       0
#XS Ineff= 2 , 0
          619.81 1056.82
Permanent Ineff=
       F       F
Bank Sta=842.7,857.15
XS Rating Curve= 0 ,0
Exp/Cntr=0.3,0.1

Type RM Length L Ch R = 1 ,150.2   ,152.7,150.2,148.4
XS GIS Cut Line= 4
     1771665.516       225147.79     1771243.641      225257.165
     1771267.079      226296.228     1771506.662      226376.957
#Sta/Elev= 30
       0 1068.66  100.03 1062.46  147.311058.824   193.7 1054.24   397.1  1054.4
   435.8 1052.43   465.2    1052   504.5 1049.27   533.9 1049.59   573.1 1051.57
  669.63  1051.2  875.24 1049.22   886.8 1049.12  890.38 1049.22  942.021051.031
  966.361051.392 1003.621051.646 1123.13 1052.22 1136.391052.202  1288.9 1051.46
 1506.571054.336  1533.5  1054.1  1611.3 1050.93  1640.4 1050.53  1650.2 1051.35
  1659.9 1054.59 1668.811059.183  1689.1 1069.06 1715.241080.093    1728 1083.04
#Mann= 14 ,-1 , 0
       0     .06       0  100.03    .016       0  147.31     .06       0
  669.63     .12       0  875.24    .045       0  890.38     .12       0
  942.02     .06       0  966.36     .12       0 1003.62     .06       0
 1123.13     .12       0 1136.39     .06       0 1506.57     .07       0
 1668.81     .12       0 1715.24    .016       0
#XS Ineff= 2 , 0
          821.05 1054.19  1125.7         1054.12
Permanent Ineff=
       F       F
Bank Sta=875.24,890.38
XS Rating Curve= 0 ,0
Exp/Cntr=0.3,0.1

Chan Stop Cuts=-1
Use User Specified Reach Order=0
Composite Channel Slope=5